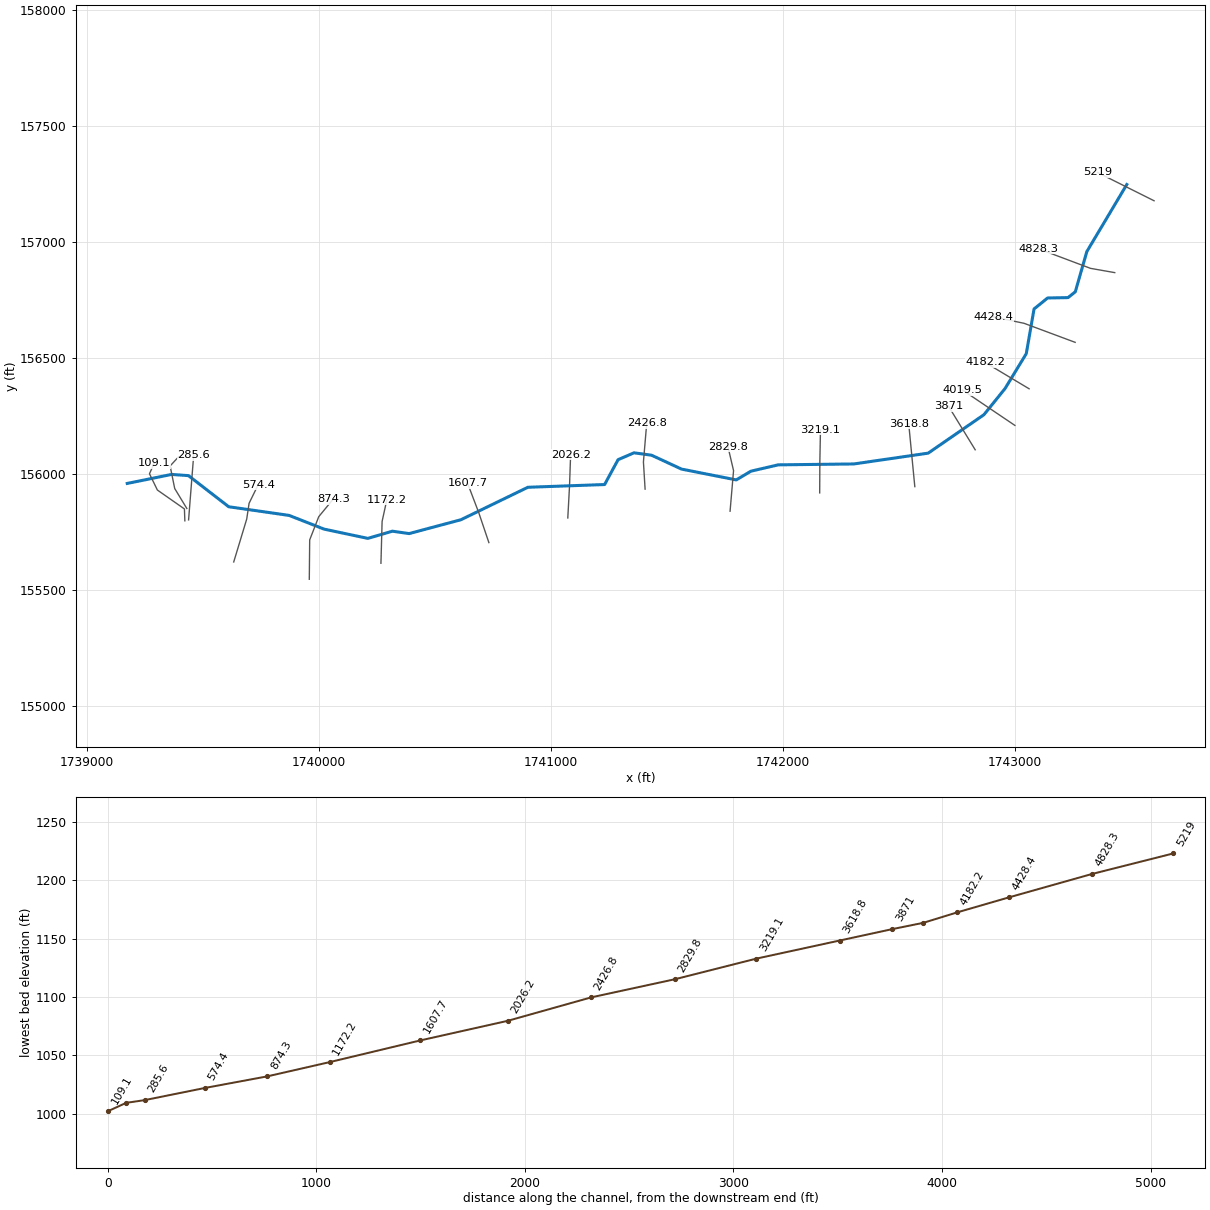
--- Mile Branch.prj (project) ---

Proj Title=Mile Branch
Current Plan=p01
Default Exp/Contr=0,0
English Units
Geom File=g01
Flow File=f01
Plan File=p01
BEGIN DESCRIPTION:
END DESCRIPTION:
DSS Export Rating Curves= 0
DSS Export Rating Curve Sorted= 0
DSS Export Volume Flow Curves= 0
DXF OffsetX= 0
DXF OffsetY= 0
DXF ScaleX= 0
DXF ScaleY= 0

--- Mile Branch.p01 (plan) ---

Plan Title=Floodplain
Program Version=4.00
Geom File=g01
Flow File=f01
K Sum by GR=0
Std Step Tol=0.01
Critical Tol=0.01
Num of Std Step Trials=20
Max Error Tol=0.3
Flow Tol Ratio=0.001
Split Flow NTrial=30
Split Flow Tol=0.02
Split Flow Ratio=0.02
Log Output Level=0
Friction Slope Method=1
Unsteady Friction Slope Method=2
Unsteady Bridges Friction Slope Method=1
Global Log Level=0
CheckData=False
Run HTab=0
Run UNet=0
Run PostProcess=0
UNET Theta=0
UNET Theta Warmup=0
UNET ZTol=0
UNET ZSATol=0
UNET MxIter=0
UNET MaxInSteps=0
UNET DtIC=0
UNET DtMin=0
UNET MaxCRTS=0
UNET WFStab=0
UNET SFStab=0
UNET WFX=0
UNET SFX=0
UNET DSS MLevel=0
UNET DZMax Abort=0
UNET Convert EG Bridges=0
UNET Use Existing IB Tables=0
UNET Froude Limit=0
UNET Froude Power=0
Write IC File=0
Echo Input=False
Echo Output=False
Write Detailed=0

--- Mile Branch.f01 (steady flow) ---

Flow Title=NFF Regression Equation
Program Version=4.00
Number of Profiles=1
Profile Names=P100yr
River Rch & RM=Mile Branch,Main      ,5219
731.7539
River Rch & RM=Mile Branch,Main      ,4182.2
755.6489
River Rch & RM=Mile Branch,Main      ,3871
897.0548
River Rch & RM=Mile Branch,Main      ,285.6
986.3485
Boundary for River Rch & Prof#=Mile Branch,Main      ,1
Up Type=0
Dn Type=3
Dn Slope=0.04814

--- Mile Branch.g01 (geometry) ---

Geom Title=Geometry
Program Version=4.00

River Reach=Mile Branch     ,Main
Reach XY= 30
     1743483.608      157248.632     1743311.238      156959.357
     1743261.595      156786.137     1743230.171      156761.092
      1743142.22      156759.494     1743083.674      156712.044
     1743050.192       156519.35     1742958.475      156368.713
     1742867.534      156256.086     1742627.194      156090.436
     1742306.987      156043.847     1741980.794      156039.979
     1741863.283      156012.788     1741799.686      155975.073
     1741563.783      156021.662     1741434.369      156081.562
     1741358.939      156091.915     1741290.141      156062.248
     1741232.074      155955.085     1740901.184      155943.274
     1740612.514      155803.298     1740389.445      155743.607
     1740316.974       155753.96     1740211.224      155722.901
      1740022.65      155762.834      1739871.79      155821.995
      1739611.38       155859.28       1739437.7       155993.56
     1739365.228      155998.737     1739173.886      155959.846

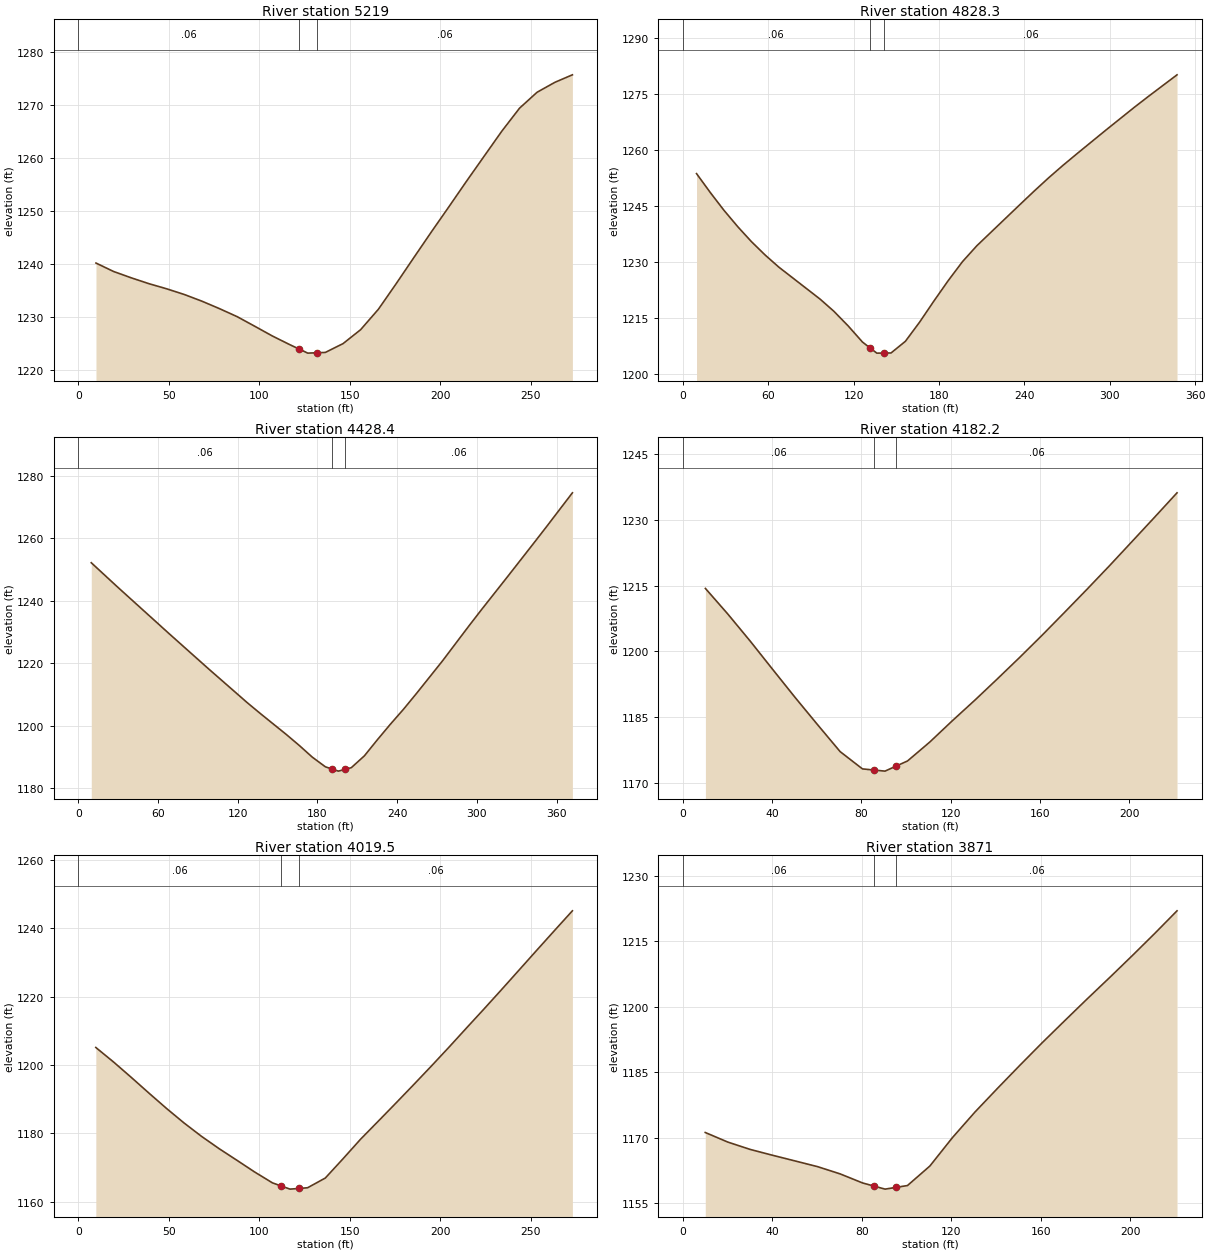
Type RM Length L Ch R = 1 ,5219    ,388.6,390.7,392.8
XS GIS Cut Line= 3
     1743601.225      157178.643     1743479.135      157239.688
     1743357.046      157300.733
#Sta/Elev= 30
     9.8 1240.21    19.5 1238.62    29.2 1237.43      39 1236.32    48.8 1235.35
    58.5 1234.28    68.3 1233.01      78  1231.6    87.8 1230.08    97.5 1228.27
   107.3 1226.42     117 1224.77   121.8    1224   126.8 1223.19   131.8 1223.26
   136.5 1223.32   146.3 1224.99     156 1227.62   165.8 1231.47   175.5 1236.24
   185.3 1241.19     195 1246.05   204.8 1250.86   214.5 1255.67   224.3 1260.43
     234 1265.13   243.8 1269.48   253.5 1272.49   263.3 1274.36     273 1275.78
#Mann= 3 , 0 , 0
       0     .06       0   121.8    .045       0   131.8     .06       0
Bank Sta=121.8,131.8
XS Rating Curve= 0 ,0
Exp/Cntr=0.3,0.1

Type RM Length L Ch R = 1 ,4828.3  ,399.7,399.9,400.2
XS GIS Cut Line= 3
     1743431.694      156868.797     1743327.156      156887.221
     1743101.466      156972.066
#Sta/Elev= 30
     9.6 1253.64    19.3 1248.56    28.9  1243.8    38.6 1239.41    48.2 1235.41
    57.9  1231.8    67.5 1228.57    96.5    1220   106.1 1216.77   116.2 1212.83
   126.2 1208.53   131.3 1207.02   136.3 1205.55   141.3 1205.57   146.3 1205.59
   156.4 1208.72   166.4 1213.86   176.5 1219.54   186.5 1224.98   196.6 1230.09
   206.6 1234.31   236.8 1245.31   246.8 1248.92   256.8 1252.42   266.9 1255.77
   276.9 1258.94     297  1265.2   317.1 1271.34   327.2 1274.32   347.3  1280.1
#Mann= 3 , 0 , 0
       0     .06       0   131.3    .045       0   141.3     .06       0
Bank Sta=131.3,141.3
XS Rating Curve= 0 ,0
Exp/Cntr=0.3,0.1

Type RM Length L Ch R = 1 ,4428.4  ,249.6,246.2,242.8
XS GIS Cut Line= 3
     1743260.976      156568.201     1743040.852      156650.204
     1742906.755      156678.394
#Sta/Elev= 26
     9.8 1252.13    29.4 1244.43    68.5 1229.38    97.9 1218.22   127.2 1207.32
     137 1203.86   156.6 1197.13   166.4  1193.6   176.2 1189.86     186 1186.78
   190.8  1186.1   195.8  1185.4   200.8 1185.97   205.5  1186.5   215.3 1190.27
   225.1 1195.43   234.9 1200.41   244.7 1205.17   254.5 1210.24   274.1 1220.68
   293.6 1231.66   303.4 1237.06     323 1247.62   342.6 1258.28   352.4 1263.66
   371.9 1274.52
#Mann= 3 , 0 , 0
       0     .06       0   190.8    .045       0   200.8     .06       0
Bank Sta=190.8,200.8
XS Rating Curve= 0 ,0
Exp/Cntr=0.3,0.1

Type RM Length L Ch R = 1 ,4182.2  ,163.8,162.6,161.4
XS GIS Cut Line= 2
     1743062.437      156367.966     1742872.383      156481.659
#Sta/Elev= 24
    10.1 1214.36    20.1 1208.54    30.2 1202.32    40.3 1195.84    50.3 1189.47
    60.4 1183.23    70.5 1177.09    80.5 1173.15    85.6 1172.89    90.6 1172.64
    95.6 1173.79   100.7 1174.96   110.7 1179.29   120.8 1184.15   130.9 1188.85
   140.9 1193.67     151 1198.62   161.1 1203.71   171.1  1208.9   181.2 1214.19
   191.3 1219.58   201.3 1225.05   211.4 1230.59   221.5 1236.19
#Mann= 3 , 0 , 0
       0     .06       0    85.6    .045       0    95.6     .06       0
Bank Sta=85.6,95.6
XS Rating Curve= 0 ,0
Exp/Cntr=0.3,0.1

Type RM Length L Ch R = 1 ,4019.5  ,157.1,148.5,139.9
XS GIS Cut Line= 3
     1743001.115      156210.003     1742887.977      156286.372
      1742774.84       156362.74
#Sta/Elev= 30
     9.7 1205.14    19.5 1200.89    29.2 1196.43      39 1191.81    48.8 1187.28
    58.5 1183.02    68.2 1179.09      78 1175.46    87.7 1172.11    97.5 1168.68
   107.3 1165.51     112 1164.62     117 1163.68     122 1163.88   126.7 1164.08
   136.5 1166.93   146.2 1172.52     156  1178.3   165.8 1183.59   175.5 1188.86
   185.2 1194.19     195 1199.65   204.8 1205.21   214.5 1210.84   224.3 1216.48
     234 1222.15   243.8 1227.95   253.5  1233.7   263.3 1239.47     273 1245.13
#Mann= 3 , 0 , 0
       0     .06       0     112    .045       0     122     .06       0
Bank Sta=112,122
XS Rating Curve= 0 ,0
Exp/Cntr=0.3,0.1

Type RM Length L Ch R = 1 ,3871    ,261.4,252.3,243.1
XS GIS Cut Line= 2
     1742829.961      156104.944     1742714.571      156293.301
#Sta/Elev= 24
      10 1171.26    20.1 1169.06    30.1 1167.38    40.2 1166.03    50.2 1164.74
    60.2 1163.44    70.3 1161.78    80.3 1159.71    85.4 1158.99    90.4 1158.29
    95.4  1158.7   100.4 1159.11   110.4 1163.57   120.5 1170.08   130.5  1175.9
   140.6 1181.34   150.6 1186.62   160.6  1191.8   170.7 1196.86   180.7 1201.83
   190.8 1206.75   200.8 1211.71   210.9 1216.82   220.9 1222.02
#Mann= 3 , 0 , 0
       0     .06       0    85.4    .045       0    95.4     .06       0
Bank Sta=85.4,95.4
XS Rating Curve= 0 ,0
Exp/Cntr=0.3,0.1

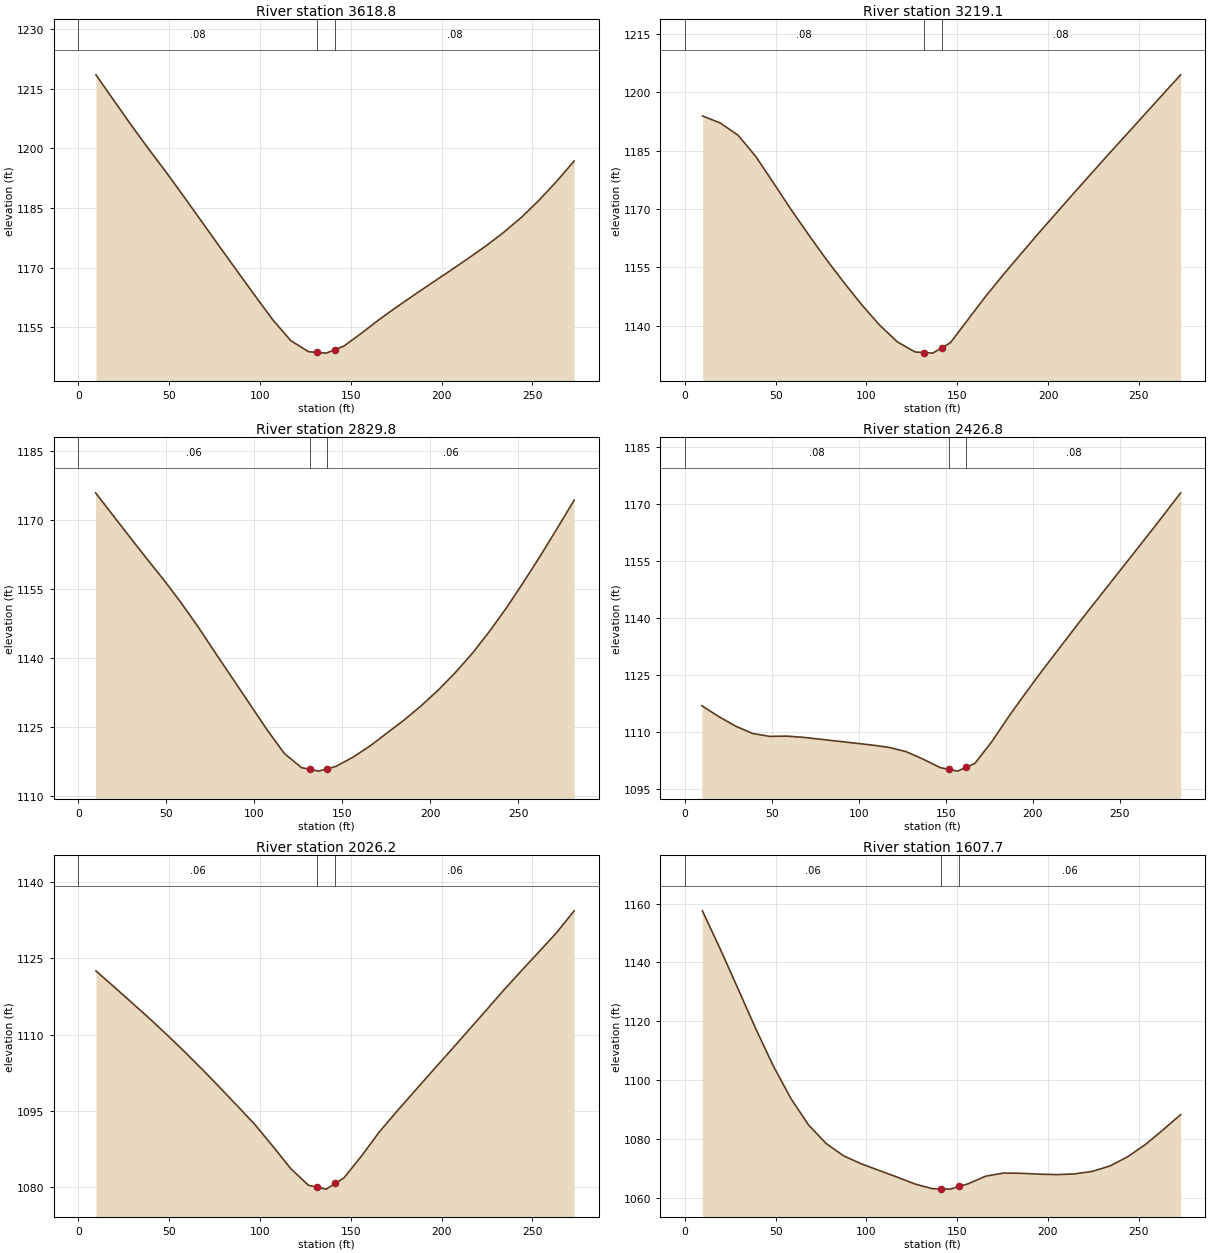
Type RM Length L Ch R = 1 ,3618.8  ,401.7,399.6,397.3
XS GIS Cut Line= 3
     1742569.589      155945.958     1742556.441      156081.824
     1742543.293      156217.689
#Sta/Elev= 30
     9.7 1218.47    19.5 1212.07    29.2 1205.78      39 1199.65    48.8 1193.71
    58.5 1187.61    68.3 1181.35      78 1175.13    87.7 1168.98    97.5 1162.81
   107.3 1156.74     117 1151.64   126.8 1148.85   131.5 1148.68   136.5  1148.5
   141.5 1149.41   146.3 1150.29     156 1153.54   165.7 1156.96   175.5 1160.17
   185.3 1163.25     195 1166.25   204.8 1169.23   214.5 1172.27   224.3 1175.41
     234 1178.79   243.8 1182.57   253.5 1186.87   263.3 1191.66     273 1196.79
#Mann= 3 , 0 , 0
       0     .08       0   131.5    .045       0   141.5     .08       0
Bank Sta=131.5,141.5
XS Rating Curve= 0 ,0
Exp/Cntr=0.3,0.1

Type RM Length L Ch R = 1 ,3219.1  ,391.2,389.3,387.7
XS GIS Cut Line= 3
     1742159.447      155919.087     1742160.196      156055.601
     1742162.821      156192.073
#Sta/Elev= 30
     9.8 1193.88    19.5 1192.09    29.3 1188.96      39 1183.54    48.8 1176.73
    58.5 1169.87    68.3  1163.3      78 1157.01    87.8 1151.03    97.5 1145.37
   107.3 1140.17     117 1135.89   126.8 1133.29   131.5 1133.14   136.5 1132.99
   141.5 1134.36   146.3 1135.69     156 1141.67   165.8 1147.66   175.5 1153.21
   185.3 1158.59     195 1163.88   204.8 1169.08   214.5 1174.24   224.3 1179.35
     234 1184.42   243.8 1189.43   253.5 1194.44   263.3 1199.48     273 1204.45
#Mann= 3 , 0 , 0
       0     .08       0   131.5    .045       0   141.5     .08       0
Bank Sta=131.5,141.5
XS Rating Curve= 0 ,0
Exp/Cntr=0.3,0.1

Type RM Length L Ch R = 1 ,2829.8  ,403,403,403
XS GIS Cut Line= 3
     1741773.028      155840.116     1741788.057      156015.008
     1741763.914      156118.349
#Sta/Elev= 27
     9.8 1175.83    29.3  1166.2      39 1161.47    48.8  1156.8    58.5 1151.89
    68.3 1146.57      78 1140.98   107.3 1124.32     117 1119.23   126.8 1116.13
   131.5 1115.76   136.5 1115.37   141.5 1115.89   146.3 1116.39     156 1118.39
   165.8 1120.86   185.2  1126.5   194.8 1129.58   204.5 1132.98   214.1 1136.75
   223.8 1140.94   233.4 1145.63   243.1 1150.78   252.7 1156.29   262.4 1162.08
     272 1168.07   281.7 1174.24
#Mann= 3 , 0 , 0
       0     .06       0   131.5    .045       0   141.5     .06       0
Bank Sta=131.5,141.5
XS Rating Curve= 0 ,0
Exp/Cntr=0.3,0.1

Type RM Length L Ch R = 1 ,2426.8  ,399.9,400.6,401.6
XS GIS Cut Line= 3
     1741406.671      155935.202     1741399.464       156052.34
     1741413.668      156219.402
#Sta/Elev= 24
     9.8 1116.93    19.6 1114.06    29.3 1111.54    39.1 1109.62    48.9 1108.87
    58.7 1108.94    68.5 1108.61   107.6  1106.6   117.4 1105.98   127.2 1104.87
   137.1 1102.87   146.9 1100.66   151.8 1100.21   156.8 1099.75   161.8 1100.77
   166.7 1101.77   176.5  1107.5   186.4 1114.22   196.3 1120.52   206.1 1126.55
   225.8  1138.3   265.3 1161.19   275.2 1166.99     285 1172.84
#Mann= 3 , 0 , 0
       0     .08       0   151.8    .045       0   161.8     .08       0
Bank Sta=151.8,161.8
XS Rating Curve= 0 ,0
Exp/Cntr=0.3,0.1

Type RM Length L Ch R = 1 ,2026.2  ,410.6,418.5,426.5
XS GIS Cut Line= 3
     1741073.373      155811.003     1741080.741      155947.299
     1741085.565      156083.743
#Sta/Elev= 30
     9.7 1122.52    19.5 1119.45    29.2 1116.36      39 1113.23    48.7    1110
    58.5 1106.64    68.2 1103.18      78 1099.57    87.7 1095.94    97.5 1092.21
   107.2 1088.01     117 1083.65   126.7 1080.39   131.5 1080.01   136.5 1079.63
   141.5 1080.76   146.2 1081.82     156 1086.18   165.8 1090.91   175.5 1094.96
   185.3 1098.94     195 1102.87   204.8 1106.78   214.5 1110.71   224.3 1114.68
     234 1118.65   243.8 1122.49   253.5 1126.22   263.3 1130.03     273 1134.33
#Mann= 3 , 0 , 0
       0     .06       0   131.5    .045       0   141.5     .06       0
Bank Sta=131.5,141.5
XS Rating Curve= 0 ,0
Exp/Cntr=0.3,0.1

Type RM Length L Ch R = 1 ,1607.7  ,443.2,435.6,427.5
XS GIS Cut Line= 3
     1740733.082      155704.735     1740689.378      155834.027
     1740640.799      155961.716
#Sta/Elev= 30
     9.7 1157.57    19.5 1144.61    29.2 1131.22      39 1117.56    48.7 1104.84
    58.5 1093.65    68.2 1084.66      78 1078.31    87.7 1074.11    97.5 1071.41
   107.2 1069.17     117 1066.94   126.7 1064.62   136.5 1062.99   141.2 1062.93
   146.2 1062.86   151.2 1063.79     156 1064.67   165.8 1067.28   175.5 1068.32
   185.3 1068.25     195 1067.95   204.8  1067.8   214.5 1068.02   224.3 1068.88
   234.1 1070.72   243.8 1073.83   253.6    1078   263.3 1082.96   273.1 1088.22
#Mann= 3 , 0 , 0
       0     .06       0   141.2    .045       0   151.2     .06       0
Bank Sta=141.2,151.2
XS Rating Curve= 0 ,0
Exp/Cntr=0.3,0.1

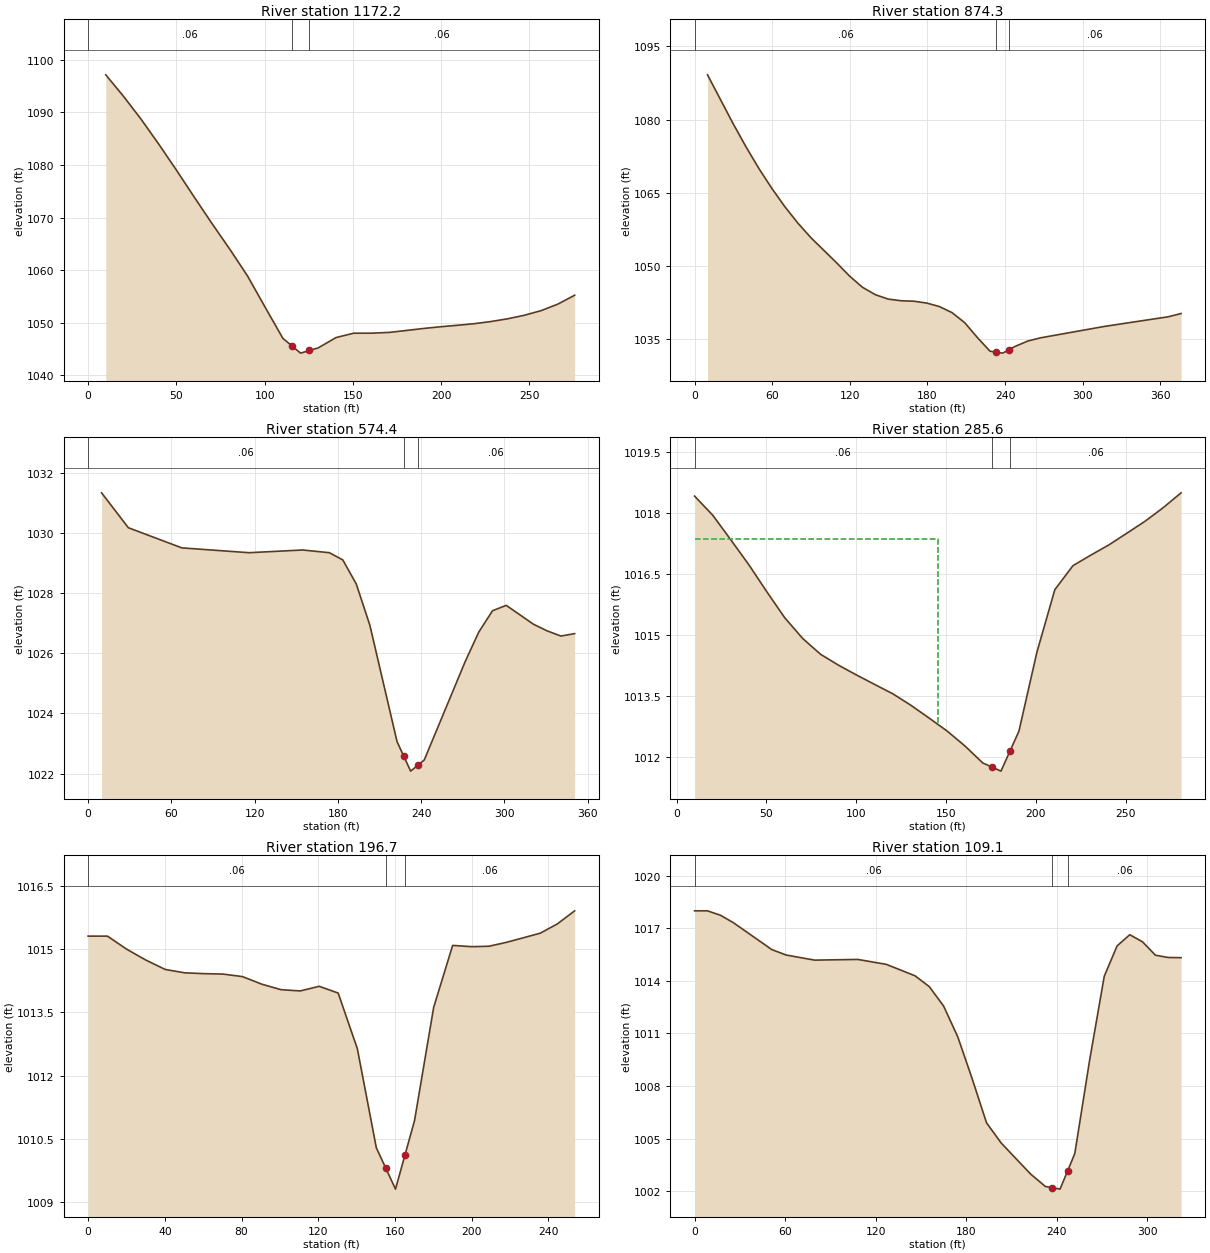
Type RM Length L Ch R = 1 ,1172.2  ,304.4,297.9,291.3
XS GIS Cut Line= 3
     1740267.716      155615.578     1740272.714      155796.106
      1740293.02      155888.996
#Sta/Elev= 30
      10 1097.15    20.1 1093.05    30.1 1088.67    40.1 1083.94    50.2 1078.95
    60.2 1073.87    70.2 1068.87    80.3 1063.98    90.3 1058.92   100.3 1052.96
   110.4 1047.02   115.4 1045.62   120.4 1044.22   125.4 1044.72   130.4 1045.22
   140.5 1047.18   150.5 1048.01   160.5 1048.01   170.6 1048.16   180.6 1048.54
   190.1 1048.91   199.6 1049.23   209.1 1049.51   218.6 1049.81   228.1 1050.22
   237.6 1050.74   247.2 1051.42   256.7  1052.3   266.2 1053.54   275.7 1055.23
#Mann= 3 , 0 , 0
       0     .06       0   115.4    .045       0   125.4     .06       0
Bank Sta=115.4,125.4
XS Rating Curve= 0 ,0
Exp/Cntr=0.3,0.1

Type RM Length L Ch R = 1 ,874.3   ,295.4,299.9,304.4
XS GIS Cut Line= 4
     1739958.786       155546.66     1739960.483      155716.351
     1739999.512      155816.469     1740062.298       155892.83
#Sta/Elev= 30
      10 1089.17    29.9 1079.09    39.9 1074.32    49.9 1069.86    59.9 1065.79
    69.9 1062.06    79.9 1058.72    89.8 1055.77   109.8 1050.58   119.8 1047.86
   129.8 1045.56   139.8 1044.03   149.7 1043.14   159.7  1042.8   169.7  1042.7
   179.5 1042.32   189.2 1041.61     199 1040.36   208.8 1038.29   218.5 1035.27
   228.3 1032.45   233.1 1032.25   238.1 1032.05   243.1 1032.76   247.8 1033.44
   257.6 1034.54   267.4 1035.19   316.7 1037.53   366.1 1039.51     376 1040.18
#Mann= 3 , 0 , 0
       0     .06       0   233.1    .045       0   243.1     .06       0
Bank Sta=233.1,243.1
XS Rating Curve= 0 ,0
Exp/Cntr=0.3,0.1

Type RM Length L Ch R = 1 ,574.4   ,287.2,288.8,290.5
XS GIS Cut Line= 4
     1739632.979      155621.324     1739688.977      155806.288
     1739699.158      155874.164     1739738.187      155953.919
#Sta/Elev= 22
     9.7 1031.33      29 1030.17    67.6  1029.5     116 1029.34   154.6 1029.43
   173.9 1029.34   183.6  1029.1   193.3  1028.3   203.1 1026.93   222.7 1023.06
   227.5 1022.58   232.5 1022.08   237.5 1022.27   242.3 1022.45   271.8 1025.72
   281.6  1026.7   291.5 1027.41   301.4 1027.59   321.1 1026.96     331 1026.74
   340.8 1026.57   350.7 1026.65
#Mann= 3 , 0 , 0
       0     .06       0   227.5    .045       0   237.5     .06       0
Bank Sta=227.5,237.5
XS Rating Curve= 0 ,0
Exp/Cntr=0.3,0.1

Type RM Length L Ch R = 1 ,285.6   ,83.6,88.9,94.2
XS GIS Cut Line= 2
     1739438.332      155802.654     1739460.392      156082.645
#Sta/Elev= 30
      10 1018.41    20.1 1017.94    30.1 1017.34    40.1 1016.73    50.2 1016.06
    60.2 1015.42    70.2 1014.91    80.2 1014.52    90.3 1014.25   100.3 1014.01
   110.3 1013.78   120.4 1013.55   130.4 1013.27   140.4 1012.96   150.5 1012.64
   160.5 1012.27   170.5 1011.85   175.6 1011.75   180.6 1011.65   185.6 1012.14
   190.6 1012.63   200.6 1014.57   210.6 1016.11   220.7  1016.7   230.7 1016.96
   240.7 1017.21   250.8  1017.5   260.8 1017.79   270.8 1018.12   280.9 1018.49
#Mann= 3 , 0 , 0
      10     .06       0   175.6    .045       0   185.6     .06       0
#XS Ineff= 2 , 0
          145.47 1017.35
Permanent Ineff=
       F       F
Bank Sta=175.6,185.6
XS Rating Curve= 0 ,0
Exp/Cntr=0.3,0.1

Type RM Length L Ch R = 1 ,196.7   ,82.6,87.5,92.6
XS GIS Cut Line= 4
     1739430.754      155851.776     1739378.528      155937.781
     1739358.632      156035.201     1739395.061      156074.543
#Sta/Elev= 29
       0 1015.31    10.1 1015.31    20.1    1015    30.2 1014.74    40.2 1014.52
    50.3 1014.44    60.4 1014.42    70.4 1014.41    80.5 1014.35    90.6 1014.17
   100.6 1014.04   110.6 1014.01   120.5 1014.12   130.4 1013.96   140.4 1012.64
   150.3 1010.29   155.3  1009.8   160.3 1009.31   165.3 1010.13   170.2 1010.93
   180.2 1013.62   190.1 1015.09   200.1 1015.06     209 1015.07   217.9 1015.16
   226.9 1015.27   235.8 1015.38   244.7  1015.6   253.7 1015.91
#Mann= 3 , 0 , 0
       0     .06       0   155.3    .045       0   165.3     .06       0
Bank Sta=155.3,165.3
XS Rating Curve= 0 ,0
Exp/Cntr=0.3,0.1

Type RM Length L Ch R = 1 ,109.1   ,116,109.1,102.3
XS GIS Cut Line= 5
     1739422.227      155798.716     1739420.332      155849.881
      1739303.79      155931.365      1739269.68       156001.48
     1739290.525      156047.907
#Sta/Elev= 30
       0 1017.99     8.5 1017.99    17.1 1017.74    25.6 1017.32    51.2 1015.78
    60.7 1015.47    79.6 1015.18   108.1 1015.22     127 1014.94     146 1014.29
   155.5 1013.67     165 1012.56   174.4  1010.8   183.9 1008.42   193.4 1005.91
   203.1 1004.76   222.6 1002.99   232.4 1002.28   237.1 1002.21   242.1 1002.13
   247.1 1003.16   251.9 1004.16   261.6 1009.42   271.4 1014.26   279.9 1015.99
   288.3 1016.63   296.8 1016.22   305.3 1015.46   313.8 1015.33   322.3 1015.32
#Mann= 3 , 0 , 0
       0     .06       0   237.1    .045       0   247.1     .06       0
Bank Sta=237.1,247.1
XS Rating Curve= 0 ,0
Exp/Cntr=0.3,0.1
Stream Node=Mile Branch     ,Main            , 0 , 0 ,Upstream end
Stream Node=Mile Branch     ,Main            , 0 , 1 ,Downstream end

Chan Stop Cuts=-1
Use User Specified Reach Order=0